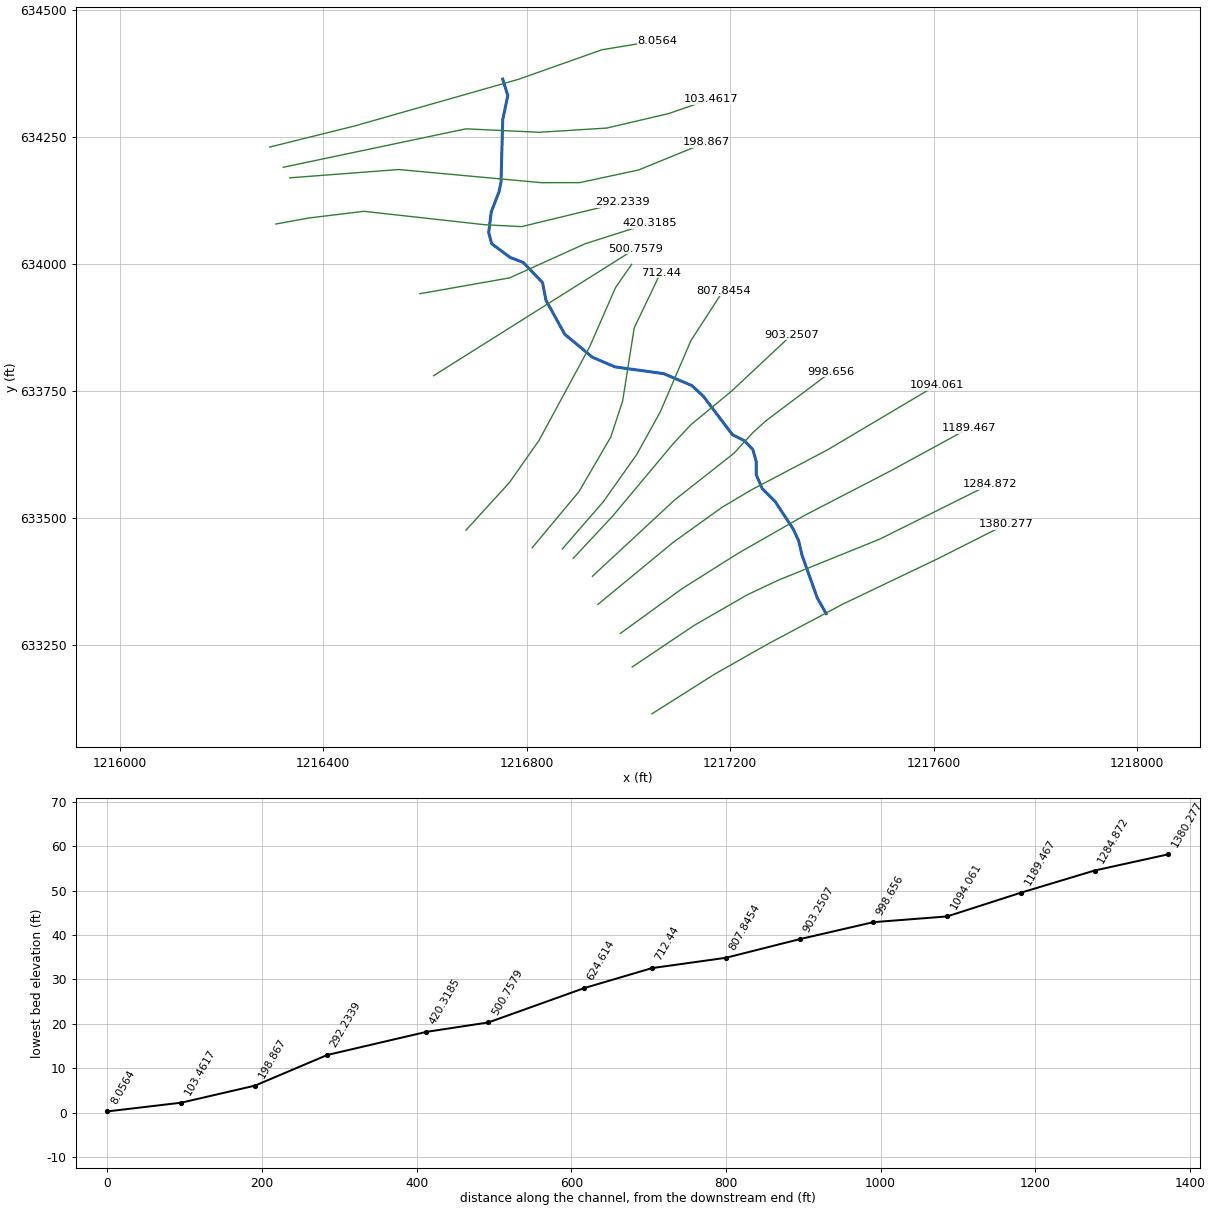
--- 524_ras.prj (project) ---

Proj Title=524
Current Plan=p01
Default Exp/Contr=0.3,0.1
English Units
Geom File=g01
Flow File=f01
Plan File=p01
Y Axis Title=Elevation
X Axis Title(PF)=Main Channel Distance
X Axis Title(XS)=Station
BEGIN DESCRIPTION:
RFD model 524 exported to HEC-RAS
END DESCRIPTION:

--- 524_ras.p01 (plan) ---

Plan Title=Plan 01
Program Version=4.10
Short Identifier=Plan 01
Geom File=g01
Flow File=f01
Subcritical Flow
Calc Critical at every XS
Secant Critical Depth

--- 524_ras.f01 (steady flow) ---

Flow Title=Flow 01
Program Version=5.01
Number of Profiles= 5
Profile Names=10yr,25yr,50yr,100yr,500yr
River Rch & RM=524,15,1380.277
  674.62  873.89 1061.51 1230.73 1606.13
River Rch & RM=524,15,1284.872
  676.48  876.65 1064.96 1235.23 1612.85
River Rch & RM=524,15,1189.467
   678.7  879.95 1069.08 1240.61 1620.89
River Rch & RM=524,15, 998.656
  683.47  887.05 1077.95  1252.2 1638.21
River Rch & RM=524,15,903.2507
  688.19  894.07 1086.74  1263.7 1655.41
River Rch & RM=524,15,807.8454
  691.07  898.37 1092.11 1270.72 1665.93
River Rch & RM=524,15,  712.44
  694.65   903.7 1098.78 1279.46 1679.02
River Rch & RM=524,15, 624.614
  697.14   907.4 1103.42 1285.54 1688.15
River Rch & RM=524,15,500.7579
  699.26  910.57 1107.37 1290.73 1695.94
River Rch & RM=524,15,420.3185
  705.56  919.98 1119.16  1306.2 1719.19
River Rch & RM=524,15,292.2339
  706.95  922.06 1121.75 1309.61 1724.32
River Rch & RM=524,15, 198.867
  708.33  924.13 1124.35 1313.02 1729.45
River Rch & RM=524,15,103.4617
  710.75  927.74 1128.86 1318.96  1738.4
River Rch & RM=524,15,  8.0564
  713.15  931.33 1133.36 1324.87 1747.31
Boundary for River Rch & Prof#=524,15,1
Up Type= 0
Dn Type= 2
Boundary for River Rch & Prof#=524,15,2
Up Type= 0
Dn Type= 2
Boundary for River Rch & Prof#=524,15,2
Up Type= 0
Dn Type= 2
Boundary for River Rch & Prof#=524,15,2
Up Type= 0
Dn Type= 2
Boundary for River Rch & Prof#=524,15,2
Up Type= 0
Dn Type= 2

--- 524_ras.g01 (geometry) ---

Geom Title=524
Program Version=4.10

River Reach=524,15
Reach XY= 30
1217388.62334257633312.6655133071217371.12334865633343.498837993
1217341.12335992633427.6654805541217334.45669606633455.998805642
1217323.62336653633479.3321323991217288.62337843633532.665450901
1217262.79005349633558.4987773151217251.12339103633585.998769477
1217251.12339178633611.8320951461217244.45672774633635.165421769
1217227.79006654 633652.665417031217204.45674035 633664.33208093
 1217146.9567596633740.1653934121217124.45676675633760.998721227
1217069.45678374633784.3320492361216973.62347895633797.665381372
1216929.25425473633816.4783090351216874.68164447633861.815554515
1216837.74018517633928.9818441271216831.02355623 633963.40456754
1216793.24251831634002.8647626791216767.21558112634012.939706117
1216731.11370045634039.8062219471216725.23665014634061.635266066
1216730.29022625634102.665297896  1216745.290223634140.998619437
1216749.45688903634160.9986133721216752.79022488634283.498576924
 1216762.7902233 634330.998562531216752.79022723634363.498553157

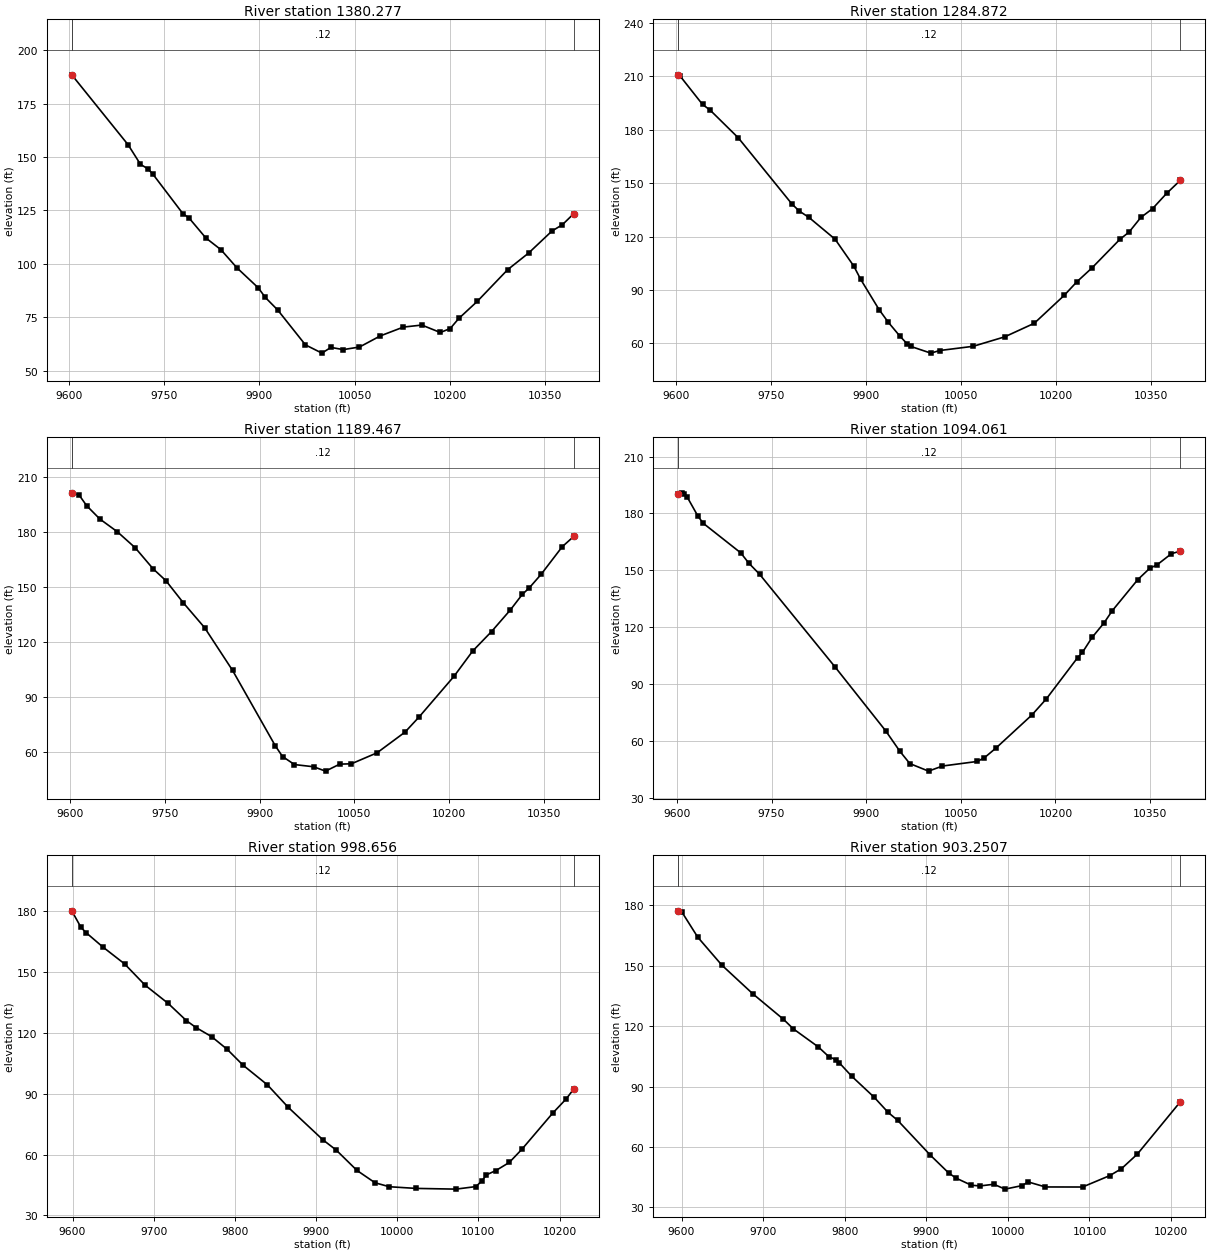
Type RM Length L Ch R = 1 ,1380.277,95.405300,95.405300,95.405300
XS GIS Cut Line= 6
1217046.23175376633115.7613792341217169.90369703633194.012200094
1217274.90328094633253.4483979381217421.48571137633331.398297264
1217609.55615656633421.3127619841217742.46924996633488.454133527
#Sta/Elev= 30
9604.814188.51089693.513155.76449712.925146.62999724.572144.51329732.337142.0754
9779.614123.56999789.432121.48229815.822112.15689839.555106.66439864.83298.16416
 9898.3688.799329909.50184.293929928.92378.446059972.63562.093569998.631 58.2227
10012.7760.9066810032.14 59.871510057.73 61.076910090.4566.2742410126.8270.41347
10155.9171.36353   1018567.8810310200.5969.74748 10214.174.4516110243.1982.45953
10290.9497.2703110324.02 105.08410360.78115.3843 10377.2118.347910395.21123.5456
#Mann= 3 , 0 , 0
9604.814    0.12       09604.814    0.12       010395.21    0.12       0
#XS Ineff= 2 , 0
       0                               0
Bank Sta=9604.814,10395.21
Exp/Cntr=0.3,0.1

Type RM Length L Ch R = 1 ,1284.872,95.405300,95.405300,95.405300
XS GIS Cut Line= 6
1217007.27105108633207.7178240871217129.79010842633289.945853055
1217234.35852022633350.0910909361217295.76793674633378.916336393
1217494.47372567633459.3519329711217711.41959938633567.303872518
#Sta/Elev= 30
9603.616210.82749606.467210.18229642.028194.16919653.882191.04269698.369175.4791
9783.266138.24289794.759134.33769810.084130.73959851.282118.53639880.908103.3836
9891.78195.948889920.77678.985759935.27371.908939953.04664.337459965.461 59.6218
9970.70758.3416710002.4954.5638510016.5556.0293610069.28 58.391610119.1363.70654
10165.7971.3218710213.0987.0038810232.95 94.580510256.75 102.34610300.85118.4062
 10315.6 122.57510334.05130.7491 10352.5135.659210374.63144.198710396.41151.5927
#Mann= 3 , 0 , 0
9603.616    0.12       09603.616    0.12       010396.41    0.12       0
#XS Ineff= 2 , 0
       0                               0
Bank Sta=9603.616,10396.41
Exp/Cntr=0.3,0.1

Type RM Length L Ch R = 1 ,1189.467,95.405400,95.405400,95.405400
XS GIS Cut Line= 6
1216983.99609909633273.7500525511217105.95048845633362.084606042
1217216.43623285633431.7629336221217345.05124907633505.134215072
1217517.38081474633594.3472672821217668.70624034633676.876064593
#Sta/Elev= 30
9602.147201.42029613.554200.32299625.707194.4161 9646.71187.1067 9674.32180.1927
9702.677171.44459731.035159.9646 9751.29153.51129778.816141.47249812.727127.8239
9856.892104.58079924.86463.287529936.21357.526469955.12753.14429 9985.3951.95032
10004.2849.5647210026.8153.3704610045.36 53.5759   10086 59.558110130.3370.86133
 10152.5 79.076410207.91101.291710237.61 115.125 10267.5125.7508 10297.4137.5807
10316.09145.9604 10327.3149.582810345.98156.939110379.61172.064610397.87177.6687
#Mann= 3 , 0 , 0
9602.147    0.12       09602.147    0.12       010397.87    0.12       0
#XS Ineff= 2 , 0
       0                               0
Bank Sta=9602.147,10397.87
Exp/Cntr=0.3,0.1

Type RM Length L Ch R = 1 ,1094.061,95.405300,95.405300,95.405300
XS GIS Cut Line= 6
 1216939.7628935633330.638216836   1217088.56656633453.266565528
1217184.03909274 633521.709019331217240.58328082633555.366090625
1217390.45389618 633634.10809217 1217605.6457282633761.823621703
#Sta/Elev= 30
9602.169190.41589607.688  190.87 9611.94190.27089616.191188.75369633.196178.6834
9641.699 174.8479701.218159.23679713.972153.82899730.977148.0049 9851.1798.91352
 9930.9865.425069953.47754.65344 9969.16 48.19549998.86144.2138510020.91 46.9005
10076.2149.3193610087.4451.2815110106.16 56.5037 10162.673.7890110185.4982.25886
10235.09104.001310242.72106.766510257.98114.640710277.06 122.35910289.88128.6849
10330.47145.141910349.54151.128610360.99 152.91410383.88158.826510397.86160.1028
#Mann= 3 , 0 , 0
9602.169    0.12       09602.169    0.12       010397.86    0.12       0
#XS Ineff= 2 , 0
       0                               0
Bank Sta=9602.169,10397.86
Exp/Cntr=0.3,0.1

Type RM Length L Ch R = 1 , 998.656,95.405300,95.405300,95.405300
XS GIS Cut Line= 6
1216929.11617422633386.1003862381217090.50176382633535.883689894
1217207.78453974633628.2429278461217244.53503113 633668.59853681
1217270.83489917633692.1799410291217397.98903046633787.818777625
#Sta/Elev= 30
9599.091180.33199610.475172.12569617.048 169.4419637.332162.49679664.189154.1167
9689.391143.63769717.902134.59569740.283126.12979752.088122.7172 9771.38118.2069
9790.671111.90999809.962104.17139840.15394.383929865.80983.289239908.61667.21403
9924.85162.208699950.45752.144739972.65446.065379990.367 44.097610023.1843.27747
 10072.442.9206910097.0444.1814910104.5147.0713210109.9749.9828310121.6752.11694
10138.0956.0934410153.6362.6100410191.4680.3892110208.2187.4816410217.6192.40973
#Mann= 3 , 0 , 0
9599.091    0.12       09599.091    0.12       010217.61    0.12       0
#XS Ineff= 2 , 0
       0                               0
Bank Sta=9599.091,10217.61
Exp/Cntr=0.3,0.1

Type RM Length L Ch R = 1 ,903.2507,95.405300,95.405300,95.405300
XS GIS Cut Line= 6
1216891.56314271633421.6030873661216968.96152696633504.407563916
1217087.34852378633646.0250485421217122.14832267633683.521319793
1217202.70871431633750.0875160291217320.80150434633860.607014709
#Sta/Elev= 30
9595.984177.19299600.738176.40319619.956164.08769649.435150.2397 9687.22136.0713
9724.993123.34379736.943118.65369767.756109.62999780.584104.81219789.137103.3151
9793.212101.84699808.55895.128819836.17584.66348 9853.2877.144129864.82673.25659
9905.072 55.90759927.47447.096479936.42644.568049955.224 41.02359965.83240.66664
9982.78841.500769996.49839.0846510017.3340.8292110024.8442.6592510046.0240.16006
10091.5240.1316710124.9345.8013410139.2649.2291610158.6956.4600710211.3682.40419
#Mann= 3 , 0 , 0
9595.984    0.12       09595.984    0.12       010211.36    0.12       0
#XS Ineff= 2 , 0
       0                               0
Bank Sta=9595.984,10211.36
Exp/Cntr=0.3,0.1

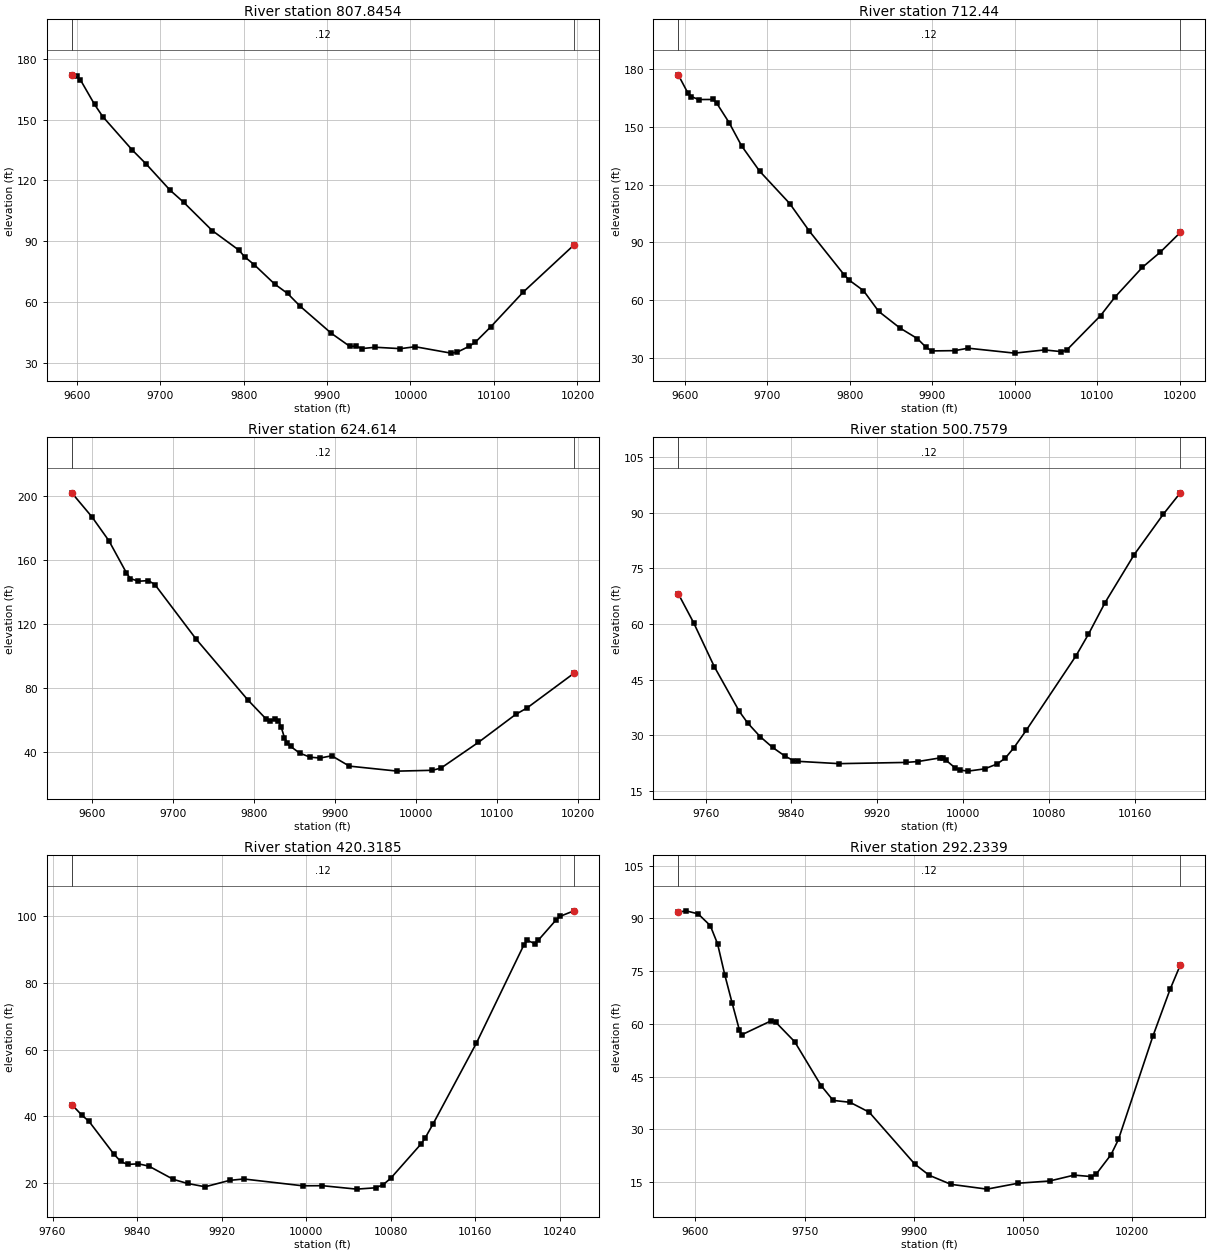
Type RM Length L Ch R = 1 ,807.8454,95.405400,95.405400,95.405400
XS GIS Cut Line= 6
1216869.93319307633439.8126031451216950.67015896633532.727292512
1217016.53095671633625.9714762381217062.78069258633709.821405564
1217122.75523897633849.3522186981217186.04868034633947.039397867
#Sta/Elev= 30
9594.091 172.0729600.067171.25949604.487169.55879621.421157.46069631.212151.4816
 9666.37135.09489683.372128.04849711.912115.19179728.065109.28479762.32195.32579
9794.48385.61827 9801.0882.424619812.97578.381559837.25868.921379852.74264.28528
9867.94757.938089905.283 44.60799927.40238.177879934.58338.341289941.76337.13628
9957.92937.778279988.01537.0952610005.6238.0427610048.4134.8869610055.67 35.2957
10070.17 38.223810077.4240.1655210096.1947.8474510135.0364.9497410195.7588.14004
#Mann= 3 , 0 , 0
9594.091    0.12       09594.091    0.12       010195.75    0.12       0
#XS Ineff= 2 , 0
       0                               0
Bank Sta=9594.091,10195.75
Exp/Cntr=0.3,0.1

Type RM Length L Ch R = 1 ,  712.44,87.826000,87.826000,87.826000
XS GIS Cut Line= 6
1216810.92787984633442.3503245861216902.69464779633552.461479657
1216965.17770934633659.6701192681216988.41826619633730.084755793
1217011.29294145633874.3447353841217063.11654825633982.702303075
#Sta/Elev= 30
9591.832176.98359603.201167.8009 9607.61165.72749616.429164.16199633.901164.1974
9638.476162.28249653.543152.16129668.657140.11799690.521126.99999726.986110.2047
9750.82195.879949792.79973.34427 9799.0970.446329816.44465.005589834.90654.22713
9860.695 45.60089881.82840.112089892.39435.565629899.25833.710849927.258 33.8668
9943.32335.137779999.63132.5694110035.9934.2236610056.1233.3605310062.8334.09862
10103.9752.0494410121.3761.6123410154.6777.0904610176.4584.9882810200.6795.18422
#Mann= 3 , 0 , 0
9591.832    0.12       09591.832    0.12       010200.67    0.12       0
#XS Ineff= 2 , 0
       0                               0
Bank Sta=9591.832,10200.67
Exp/Cntr=0.3,0.1

Type RM Length L Ch R = 1 , 624.614,123.856100,123.856100,123.856100
XS GIS Cut Line= 6
1216680.66543009 633476.753419451216766.28515464633570.667014553
 1216824.4524307633653.7086423091216923.95844018 633837.81565324
1216974.45220377633953.3519640791217006.18130034633999.219354514
#Sta/Elev= 30
9574.714202.1677 9599.67187.10649620.642172.16179642.278  152.099647.036148.5453
9657.164146.86419669.413147.2498 9677.42 144.7919728.458110.61039792.14172.69776
9815.10960.557549819.98459.260369826.33460.894879830.07659.668459833.63255.42691
9837.55949.025399841.30145.370359845.04343.568069856.26739.360519869.32236.77594
9881.589 36.25489896.041 37.6488 9917.7231.189719977.19128.0561710020.4528.57851
10031.1129.9861110077.2846.0588310123.3263.5268510137.4467.5995810195.2289.22822
#Mann= 3 , 0 , 0
9574.714    0.12       09574.714    0.12       010195.22    0.12       0
#XS Ineff= 2 , 0
       0                               0
Bank Sta=9574.714,10195.22
Exp/Cntr=0.3,0.1

Type RM Length L Ch R = 1 ,500.7579,80.439400,80.439400,80.439400
XS GIS Cut Line= 3
1216616.93100816633780.3764283961216795.76125419633892.879963458
1217013.21211675634029.731278494
#Sta/Elev= 30
 9734.4568.140869748.78260.327689768.16248.426459791.418 36.41259799.17133.29938
9810.79929.629459822.42726.713059834.05524.356569841.80723.171559845.68322.96474
9884.44422.333059946.46222.659349958.09122.911589978.10423.85981 9981.3523.72169
9984.26323.225479992.97921.105659996.85620.6177310004.6120.3178210020.1120.92526
10031.74 22.2308 10039.523.8400510047.2526.5386710058.8831.27812 10105.451.40828
10117.03 57.242510132.5365.7583910159.6778.67477 10186.8 89.560910202.6695.32627
#Mann= 3 , 0 , 0
 9734.45    0.12       0 9734.45    0.12       010202.66    0.12       0
#XS Ineff= 2 , 0
       0                               0
Bank Sta=9734.45,10202.66
Exp/Cntr=0.3,0.1

Type RM Length L Ch R = 1 ,420.3185,128.084600,128.084600,128.084600
XS GIS Cut Line= 4
1216590.06449229633941.5755234211216766.37600249633972.639932364
1216914.98141819634039.8062219471217041.75778982634080.105995715
#Sta/Elev= 30
9778.22943.527129787.84540.345739794.50838.520879817.82728.79286 9824.4926.48227
9831.15325.590849841.14725.773789851.14125.092069874.46121.091389887.78619.88449
9904.44318.889089927.76320.821659941.088 21.22489996.65419.1877710015.3919.21636
10047.7918.18522 10065.818.58666   1007319.53071 10080.221.48856   1010931.81058
 10112.633.4960210120.3437.8553510161.1461.9688410205.8991.2903210209.3392.76894
10216.2291.8330710219.6692.8000510236.87 99.022810240.3299.9732410253.36 101.633
#Mann= 3 , 0 , 0
9778.229    0.12       09778.229    0.12       010253.36    0.12       0
#XS Ineff= 2 , 0
       0                               0
Bank Sta=9778.229,10253.36
Exp/Cntr=0.3,0.1

Type RM Length L Ch R = 1 ,292.2339,93.366900,93.366900,93.366900
XS GIS Cut Line= 6
1216306.90157786634078.5693329571216370.99070722634090.291845828
1216480.05078402634103.497354656 1216718.2069492634077.073604941
1216789.88420382634073.389366731 1216987.1851795634121.245348066
#Sta/Elev= 30
9576.44791.751489587.10292.145329603.77991.278729620.45587.940149630.46182.75888
9640.46773.847499650.40865.952939660.34258.311329663.65356.884619703.38860.79238
9710.01160.534679736.418 54.89259772.67242.41944 9789.1738.215439812.26737.68232
9838.66434.867889901.35820.082819921.17816.904199950.908 14.341310000.41 12.9773
10043.1114.6534710086.4515.2903810120.2116.9665510143.8516.54422 10150.617.30736
10170.8522.8093110180.98 27.126910228.2456.4815110251.8869.8171410265.9176.73132
#Mann= 3 , 0 , 0
9576.447    0.12       09576.447    0.12       010265.91    0.12       0
#XS Ineff= 2 , 0
       0                               0
Bank Sta=9576.447,10265.91
Exp/Cntr=0.3,0.1

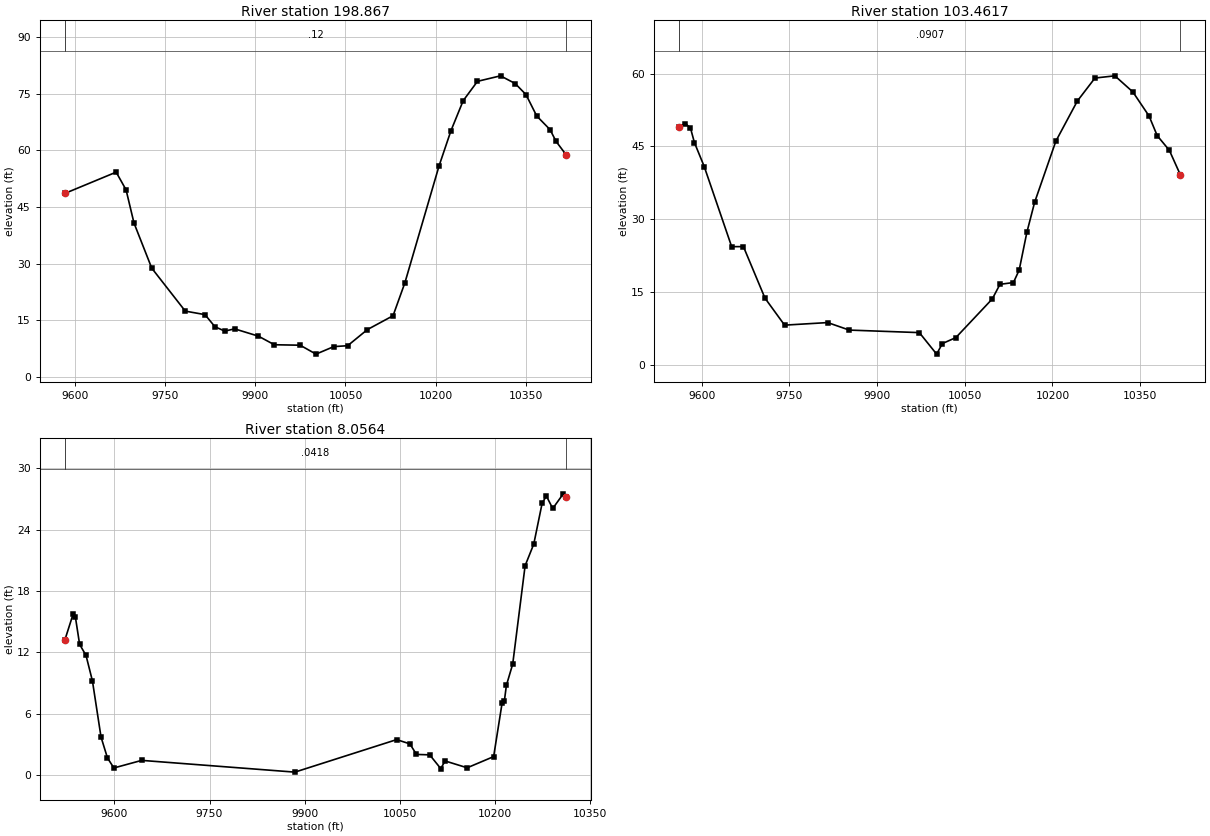
Type RM Length L Ch R = 1 , 198.867,95.405300,95.405300,95.405300
XS GIS Cut Line= 6
 1216334.2407268634169.3423331641216548.18789099634185.640185508
1216829.23002408634159.7492555821216904.07939183 634159.87183081
1217019.90650299634184.7699662121217152.80099314634238.982359634
#Sta/Elev= 30
9582.82448.59347 9668.2354.221879684.74249.53468 9697.9340.755979727.51128.81201
9783.31317.451639816.14516.52343 9832.5713.331279848.994 12.16519865.41812.75984
9905.093  10.8259931.5528.5544319974.5488.43148110000.896.07237310030.538.064413
10053.588.29828810086.4912.5696710129.1716.2326310148.8724.9477510205.7855.89488
10225.5465.1762810245.93 73.136410269.7178.2493310308.0579.7062510332.5677.65604
10350.4574.7436710368.3469.0798610390.5365.4687310400.5562.3563110417.13 58.8436
#Mann= 3 , 0 , 0
9582.824    0.12       09582.824    0.12       010417.13    0.12       0
#XS Ineff= 2 , 0
       0                               0
Bank Sta=9582.824,10417.13
Exp/Cntr=0.3,0.1

Type RM Length L Ch R = 1 ,103.4617,95.405300,95.405300,95.405300
XS GIS Cut Line= 6
1216321.39933392634190.0907949061216680.73898327  634265.6528707
1216824.51336193634258.8372069751216957.13606128634267.143244103
1217078.81066787634295.5578034971217161.92113489 634324.21664542
#Sta/Elev= 30
9561.656 49.01819572.28449.70103 9581.02 48.77299587.72545.788179604.48840.85579
9651.42424.355719671.53924.365189708.41813.752559741.944 8.195449815.7018.723354
9852.5797.1776779972.3826.65717410001.95 2.22708 10011.84.40447710034.795.629248
10097.1613.5978310110.2816.6016110133.2716.9646410143.1319.5385110156.2827.30802
10169.4933.4707910205.82 46.072210242.6254.3477910272.7359.0754210306.7459.53089
 10337.556.2180810365.2651.2528410379.1547.2186910399.9744.1827810418.7639.14667
#Mann= 3 , 0 , 0
9561.656  0.0907       09561.656  0.0907       010418.76  0.0907       0
#XS Ineff= 2 , 0
       09930.255                       0
Bank Sta=9561.656,10418.76
Exp/Cntr=0.3,0.1

Type RM Length L Ch R = 1 ,  8.0564,0.000000,0.000000,0.000000
XS GIS Cut Line= 5
1216294.78027731  634229.8203419 1216461.4625715634271.211247176
1216783.64042866634362.9424426111216948.08537656634421.113444611
1217056.59666875634439.012214452
#Sta/Elev= 30
 9521.6413.194249534.78815.750549538.16815.490949544.92912.77231 9555.0711.68142
9565.212 9.177999578.7343.7023359588.8751.6556669599.017 0.670999642.9631.414236
9884.7010.26428310045.363.44545910066.253.03095610076.691.99589310097.571.956075
10114.970.61307710121.931.35683710156.730.68865610198.491.78344610211.987.077059
10215.317.17618110218.638.75298510228.6110.8427210248.1720.4617810261.8622.58639
10275.1626.6115810281.8127.2762810291.7826.0631510308.4127.4986610312.7827.16489
#Mann= 3 , 0 , 0
 9521.64  0.0418       0 9521.64  0.0418       010312.78  0.0418       0
#XS Ineff= 2 , 0
       09944.505         10052.8       0
Bank Sta=9521.64,10312.78
Exp/Cntr=0.3,0.1